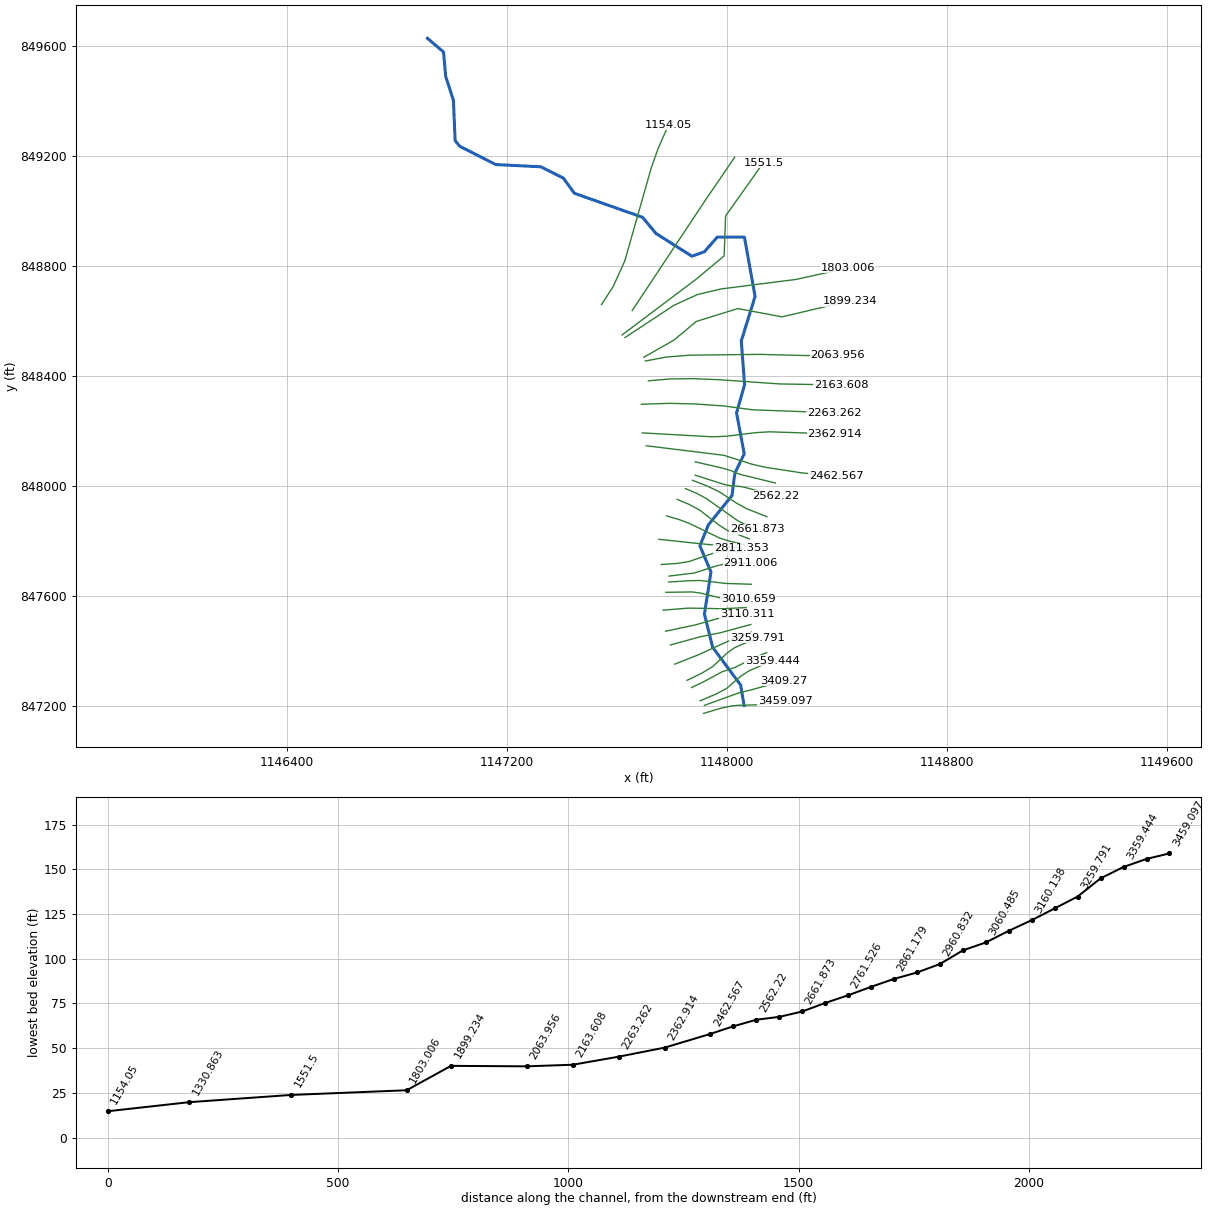
--- 69_ras.prj (project) ---

Proj Title=69
Current Plan=p01
Default Exp/Contr=0.3,0.1
English Units
Geom File=g01
Flow File=f01
Plan File=p01
Y Axis Title=Elevation
X Axis Title(PF)=Main Channel Distance
X Axis Title(XS)=Station
BEGIN DESCRIPTION:
RFD model 69 exported to HEC-RAS
END DESCRIPTION:

--- 69_ras.p01 (plan) ---

Plan Title=Plan 01
Program Version=4.10
Short Identifier=Plan 01
Geom File=g01
Flow File=f01
Subcritical Flow
Calc Critical at every XS
Secant Critical Depth

--- 69_ras.f01 (steady flow) ---

Flow Title=Flow 01
Program Version=5.01
Number of Profiles= 5
Profile Names=10yr,25yr,50yr,100yr,500yr
River Rch & RM=69,38,3459.097
   204.5  367.75  528.68  724.89 1325.31
River Rch & RM=69,38, 3409.27
  211.85  381.27  548.52   752.7  1379.1
River Rch & RM=69,38,3259.791
  217.97  392.53  565.06   775.9 1424.06
River Rch & RM=69,38,3110.311
  228.37  411.67   593.2  815.39 1500.78
River Rch & RM=69,38,3010.659
  238.14  429.68  619.69  852.61  1573.3
River Rch & RM=69,38,2861.179
  255.21  461.18  666.09  917.89 1700.89
River Rch & RM=69,38,2761.526
  258.86  467.93  676.04   931.9 1728.34
River Rch & RM=69,38,2661.873
  264.34  478.05  690.96  952.93 1769.59
River Rch & RM=69,38, 2562.22
  266.17  481.42  695.94  959.94 1783.35
River Rch & RM=69,38,2362.914
  272.85  493.79  714.19  985.67 1833.91
River Rch & RM=69,38,2163.608
  274.68  497.16  719.17  992.69 1847.72
River Rch & RM=69,38,2063.956
  463.31  848.24 1240.57 1732.79 3329.37
River Rch & RM=69,38,1899.234
  472.88  866.15 1267.31 1770.96 3406.94
River Rch & RM=69,38,1803.006
  474.67  869.51 1272.33 1778.12 3421.51
River Rch & RM=69,38,  1551.5
  750.12 1387.95 2050.55 2895.58  5728.8
River Rch & RM=69,38,1330.863
  754.25 1395.76 2062.33 2912.57 5764.33
River Rch & RM=69,38, 1154.05
  917.16 1704.51 2528.89 3587.34 7184.62
River Rch & RM=69,38,1057.837
  941.19 1750.17 2598.05 3687.61 7397.04
River Rch & RM=69,38,898.7555
   945.3 1757.97 2609.86 3704.74 7433.36
River Rch & RM=69,38,769.8262
  947.05 1761.31 2614.92 3712.08 7448.93
River Rch & RM=69,38,615.4347
  959.35 1784.69 2650.36 3763.48    7558
River Rch & RM=69,38,439.0827
   965.8 1796.94 2668.92 3790.41 7615.19
River Rch & RM=69,38,253.5101
  975.75 1815.87 2697.61 3832.05 7703.64
River Rch & RM=69,38,  46.678
  978.68 1821.43 2706.05  3844.3 7729.67
Boundary for River Rch & Prof#=69,38,1
Up Type= 0
Dn Type= 2
Boundary for River Rch & Prof#=69,38,2
Up Type= 0
Dn Type= 2
Boundary for River Rch & Prof#=69,38,2
Up Type= 0
Dn Type= 2
Boundary for River Rch & Prof#=69,38,2
Up Type= 0
Dn Type= 2
Boundary for River Rch & Prof#=69,38,2
Up Type= 0
Dn Type= 2

--- 69_ras.g01 (geometry) ---

Geom Title=69
Program Version=4.10

River Reach=69,38
Reach XY= 30
1148061.37603671847201.4833626131148048.65906392847276.142604741
1147946.87689764847413.4572097661147916.98143746847534.304677402
1147940.77123211847687.0593329831147900.56578633847782.427557839
1147931.49546001847858.8640365891148017.13417723 847965.02186399
1148027.73965454848046.8671801061148061.73983105848116.746049106
1148033.76763371848266.0548874831148063.08014458848367.658707787
1148051.05706042848527.6878777881148101.20965152848689.278498599
1148062.43803564848904.8487457041147963.69671616848904.848745704
1147917.03873008848851.680342942 1147871.4658134848835.404301256
1147741.25748008848917.8695790471147692.01193029848976.942054629
1147443.97069931849064.2717202391147404.16944378849119.417736337
1147322.23918563849160.5109024351147158.04756041849168.719465461
1147027.08704636849235.3451812221147010.51251053 849255.81441777
1147004.37735878849401.9057221041146976.12864313849489.373954341
1146968.43475086849577.7273391441146910.12497675849627.616002473

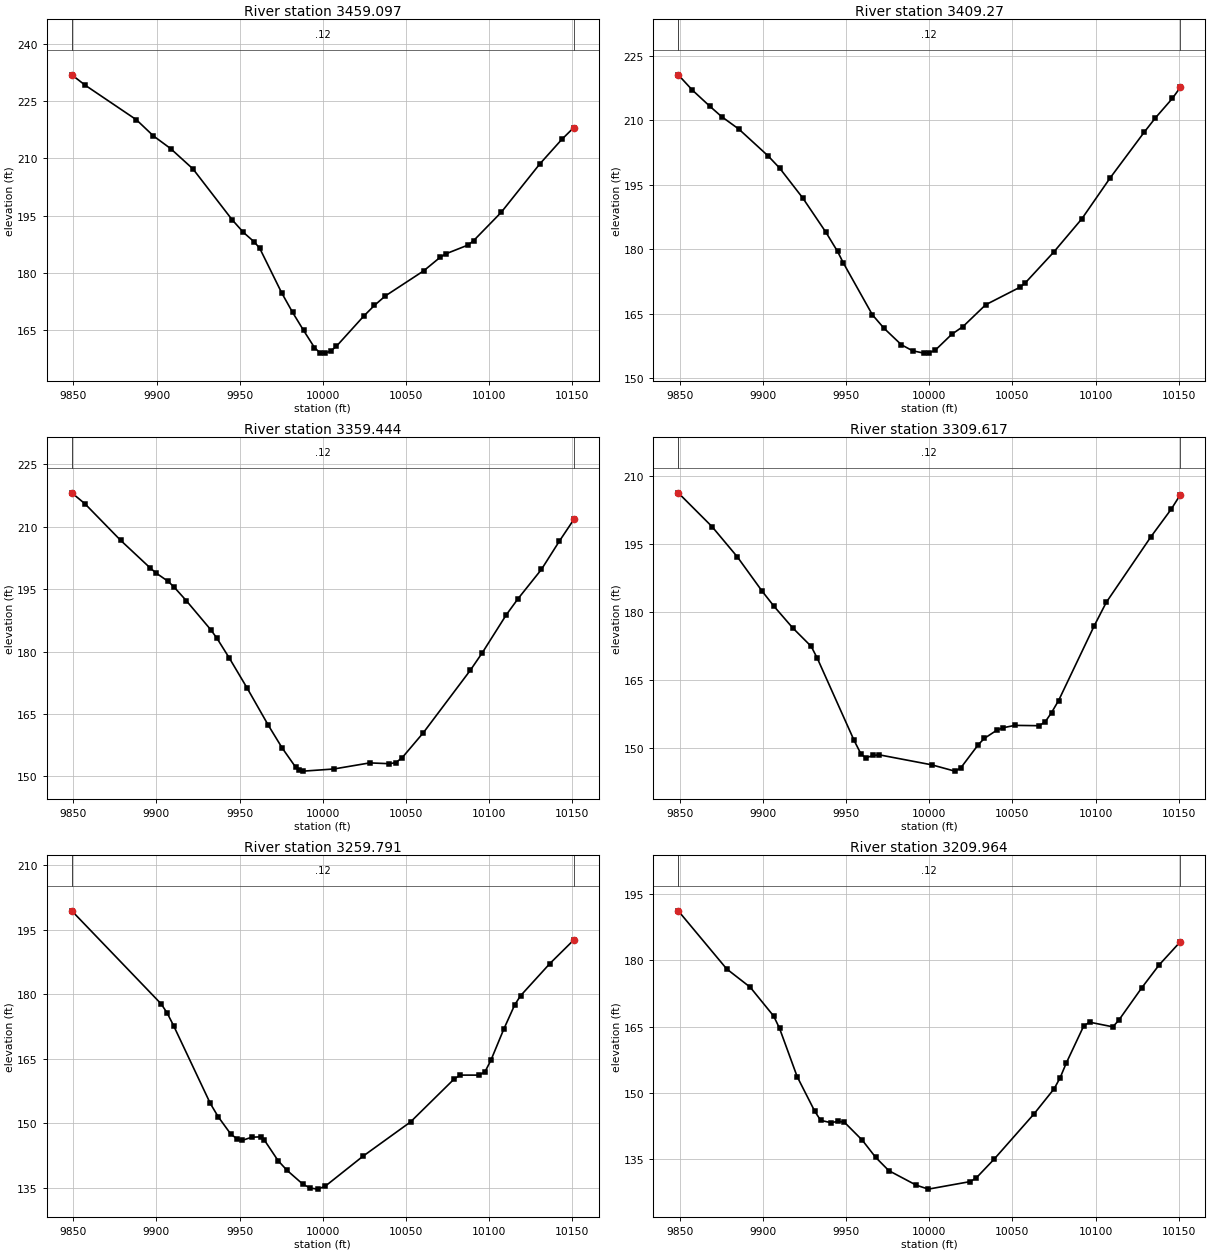
Type RM Length L Ch R = 1 ,3459.097,49.826400,49.826400,49.826400
XS GIS Cut Line= 6
1147914.16363207 847173.152465391147974.65291077847191.191802448
 1148015.9736248847200.1114320711148039.62718868847202.483120102
1148115.90469241847204.373020198 1148211.1214035847219.440441831
#Sta/Elev= 30
9849.043231.94969857.091229.22949887.904220.14679898.174215.89189908.445212.5907
9921.944207.22869945.439193.91089952.152 190.6139958.786 188.0639962.084186.3811
9975.273174.68389981.849169.54919988.411164.84819994.972160.32879998.253158.9501
10001.54158.858910004.82159.4317 10008.1160.617810024.51168.532810031.08171.4135
10037.66 173.89610060.74 180.496 10070.7184.073510074.02184.941910087.31187.2407
10090.63188.378810107.24195.814610130.49208.546410143.78215.020210150.96218.1092
#Mann= 3 , 0 , 0
9849.043    0.12       09849.043    0.12       010150.96    0.12       0
#XS Ineff= 2 , 0
       0                               0
Bank Sta=9849.043,10150.96
Exp/Cntr=0.3,0.1

Type RM Length L Ch R = 1 , 3409.27,49.826500,49.826500,49.826500
XS GIS Cut Line= 6
1147917.09612116847202.3724472211148041.93227645847247.680558881
1148058.56509213847251.9490567791148060.54676264847252.219208553
1148078.63977319847256.415751577 1148205.3698924847291.182893565
#Sta/Elev= 30
9849.024220.64159857.599217.0499 9868.07213.3022 9875.05210.92019885.521207.9751
9902.972201.77919909.952198.92869923.913 191.9379937.874183.92369944.855179.4644
9948.345176.77559965.796164.70229972.777161.57059983.205157.7269 9989.98156.3169
9996.754155.769510000.12155.897410003.47156.402610013.57160.176110020.32161.9681
10033.92167.039510054.34171.088410057.74172.139210074.75179.273610091.76187.0759
10108.77196.599710129.18207.221710135.99210.591610146.19215.128710150.99 217.721
#Mann= 3 , 0 , 0
9849.024    0.12       09849.024    0.12       010150.99    0.12       0
#XS Ineff= 2 , 0
       0                               0
Bank Sta=9849.024,10150.99
Exp/Cntr=0.3,0.1

Type RM Length L Ch R = 1 ,3359.444,49.826500,49.826500,49.826500
XS GIS Cut Line= 6
1147901.45405296847218.9375423761147959.55721469847243.596897525
 1147996.9429014 847263.316990321148049.45328044847308.493522639
1148079.65442896847328.0089240381148163.14724525847364.262317611
#Sta/Elev= 30
9849.067218.16629856.995215.5323 9878.38206.7731  9896.2200.11589899.764198.8873
9906.892196.92139910.456195.57419917.877192.26759932.642185.25829936.351183.2082
9943.769 178.4699954.454 171.2699967.132162.37299975.571156.83789983.793152.1567
9985.693 151.5159988.358151.281910006.55151.791310028.21153.260610039.93153.0692
10043.83 153.30610047.74154.526310060.42160.503910088.66175.509510095.96 179.777
10110.31188.853210117.35192.710510131.42199.750210142.11206.491110150.92211.7679
#Mann= 3 , 0 , 0
9849.067    0.12       09849.067    0.12       010150.92    0.12       0
#XS Ineff= 2 , 0
       0                               0
Bank Sta=9849.067,10150.92
Exp/Cntr=0.3,0.1

Type RM Length L Ch R = 1 ,3309.617,49.826400,49.826400,49.826400
XS GIS Cut Line= 6
1147870.12991692847267.0588200231147912.04593302 847286.96215248
1147981.05623016847324.1976753991148028.38174342847340.249944048
1148100.32662836847376.2363309751148143.45735385 847394.01993196
#Sta/Elev= 30
9849.056206.21029869.387198.76379884.548192.12499899.544184.52929906.627181.2264
9917.811176.49279928.995172.39769932.723 169.7369954.817151.66429958.818148.7782
9961.727147.82669966.274148.36419970.002 148.499 10001.5146.302810015.33144.9167
10018.79145.549110029.49150.755110033.16152.1401 10040.5153.901210044.16154.4574
 10051.5154.992210066.17154.919210069.84155.843410073.51157.803910077.75160.4548
10099.19176.924310106.45182.096410133.39196.590410145.49202.611810150.95  205.78
#Mann= 3 , 0 , 0
9849.056    0.12       09849.056    0.12       010150.95    0.12       0
#XS Ineff= 2 , 0
       0                               0
Bank Sta=9849.056,10150.95
Exp/Cntr=0.3,0.1

Type RM Length L Ch R = 1 ,3259.791,49.826500,49.826500,49.826500
XS GIS Cut Line= 6
1147853.75641333847293.3296626041147905.67617717847318.362902258
1147946.74576737847342.9940604681148000.59684034847393.590600235
1148026.49345586847411.7312049951148109.25587283847448.378492893
#Sta/Elev= 30
9849.072199.38619902.842177.74759906.484 175.5969910.299 172.6969932.358154.6295
9937.078151.54979944.729147.48079948.555146.39239951.494146.0471 9957.31146.7968
9962.591 146.8729964.731146.19349973.104141.33899978.436139.10899987.955135.8896
9992.469134.97079996.984134.729510001.43 135.405   10024142.335610052.71150.3362
10079.04160.351710082.71161.219410093.73161.2171 10097.4161.935510101.07164.7015
10108.74 171.87210115.35 177.54810118.86179.663310136.43187.118310150.89192.6345
#Mann= 3 , 0 , 0
9849.072    0.12       09849.072    0.12       010150.89    0.12       0
#XS Ineff= 2 , 0
       0                               0
Bank Sta=9849.072,10150.89
Exp/Cntr=0.3,0.1

Type RM Length L Ch R = 1 ,3209.964,49.826500,49.826500,49.826500
XS GIS Cut Line= 6
1147809.48276238847352.1053907431147894.67164875847385.996391789
1147947.74262195847410.0947661671147949.45376384847411.130137324
1148028.37301535847446.6454015771148087.97543969847468.317043543
#Sta/Elev= 30
9849.031191.23499878.187178.05039892.311173.91279906.435167.36149909.966164.5733
9920.559153.62249931.151145.76859934.682143.72399940.714143.20059945.368143.4869
9948.972143.28579959.781139.19329967.739135.33319975.674132.3141 9992.21129.0122
9999.444128.123710024.72129.840710028.32130.693410038.93134.890810062.92145.1507
10075.09150.886110078.69153.379810082.29156.634810092.92 165.16510096.41165.9812
10110.37164.929310113.86166.376510127.83173.8077 10138.3 179.00110150.96184.2154
#Mann= 3 , 0 , 0
9849.031    0.12       09849.031    0.12       010150.96    0.12       0
#XS Ineff= 2 , 0
       0                               0
Bank Sta=9849.031,10150.96
Exp/Cntr=0.3,0.1

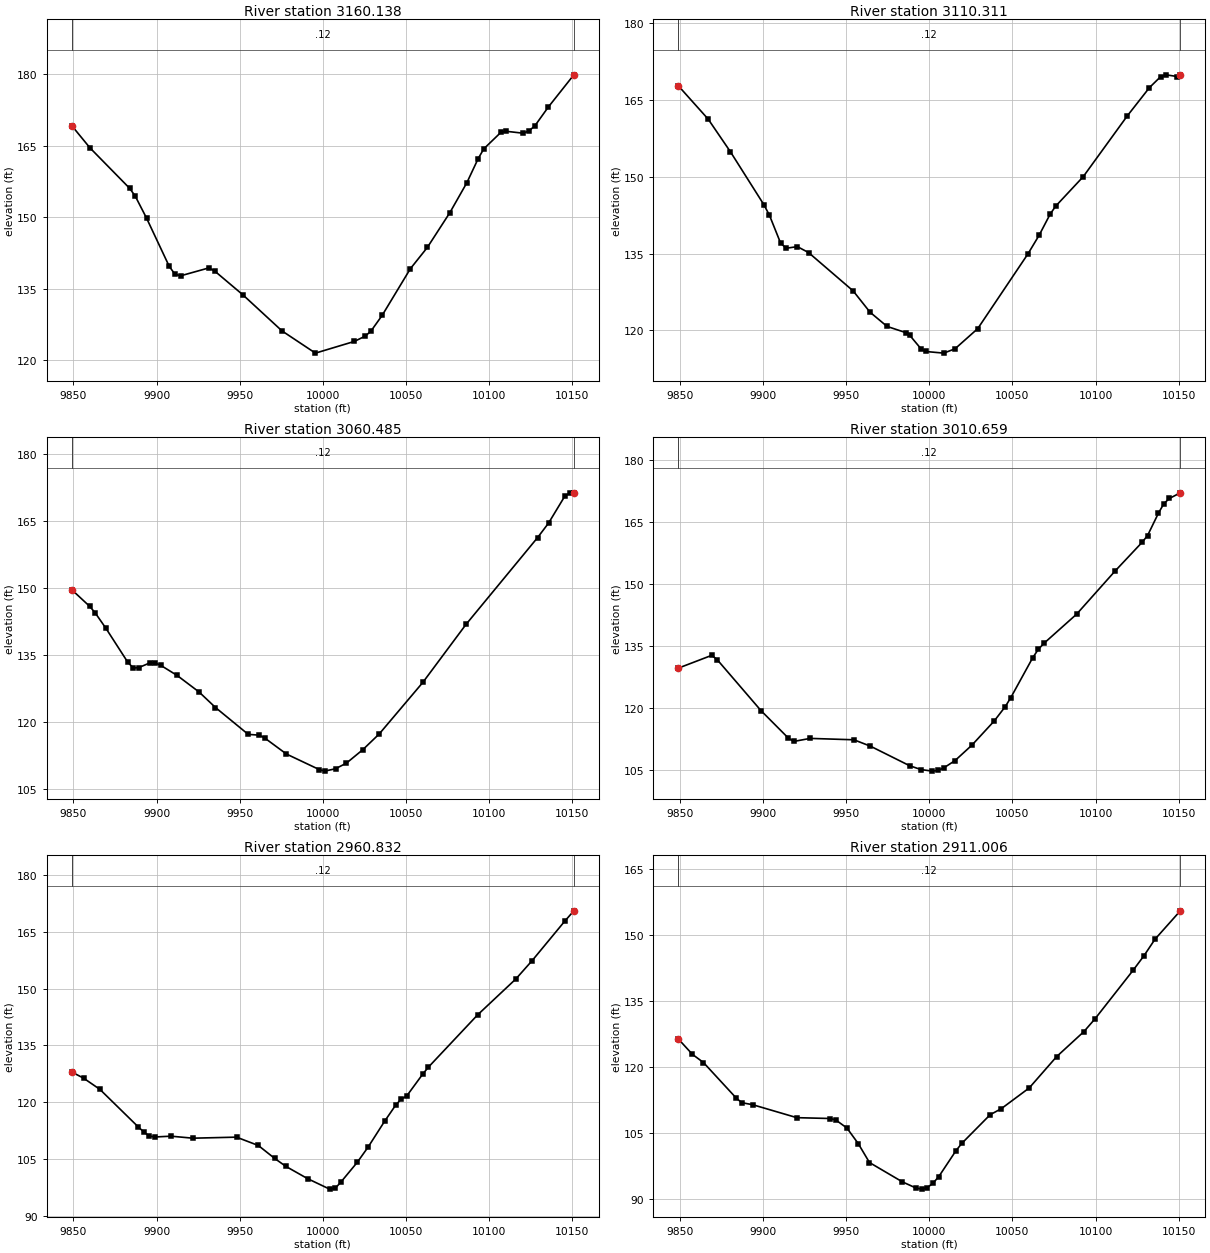
Type RM Length L Ch R = 1 ,3160.138,49.826400,49.826400,49.826400
XS GIS Cut Line= 6
1147793.22816625847421.6972595211147899.11990475847451.066625723
1147938.37330665847459.1987625231147940.35201038847459.489849355
1147973.23037478847465.7983980541148085.65243241847496.336285377
#Sta/Elev= 30
9849.024169.21999859.959 164.5679883.792156.09839887.197154.44639894.006149.8285
9907.625139.73259911.029138.08539914.434 137.7349931.457139.39339934.862138.7713
9951.886133.76399975.451126.18899995.554121.527610018.93123.976410025.62125.1144
10028.96126.154410035.66 129.42510052.66139.228710062.86143.683110076.45151.0084
10086.65157.273310093.45162.325610096.85 164.37610107.05167.800310110.45168.0339
10120.65167.632510124.05168.163910127.45169.144810135.63173.131810150.97179.8798
#Mann= 3 , 0 , 0
9849.024    0.12       09849.024    0.12       010150.97    0.12       0
#XS Ineff= 2 , 0
       0                               0
Bank Sta=9849.024,10150.97
Exp/Cntr=0.3,0.1

Type RM Length L Ch R = 1 ,3110.311,49.826500,49.826500,49.826500
XS GIS Cut Line= 6
1147776.32428195847471.9442817861147884.15986506847494.821442913
1147922.36587197847505.7887363451147924.31718967847506.227324093
 1147967.2202202847518.2118992451148071.42812543847534.064880204
#Sta/Elev= 30
9849.015167.73429867.006161.21849880.421154.83779900.544 144.5189903.898142.4474
9910.606137.0166 9913.96136.04269920.667136.34899927.375135.19869954.206127.7196
9964.357123.56889974.597120.79449985.836119.5872 9988.25 119.0569995.077116.4057
9997.727115.909510008.68115.5871 10015.5116.436310029.12120.364110059.41134.9843
10066.05 138.57310072.69142.698510076.01144.2483 10092.6150.007410119.15161.8838
10132.42 167.37310139.06169.477110142.38169.852310149.02169.524810150.95169.7732
#Mann= 3 , 0 , 0
9849.015    0.12       09849.015    0.12       010150.95    0.12       0
#XS Ineff= 2 , 0
       0                               0
Bank Sta=9849.015,10150.95
Exp/Cntr=0.3,0.1

Type RM Length L Ch R = 1 ,3060.485,49.826500,49.826500,49.826500
XS GIS Cut Line= 6
1147766.83627302847548.4392751221147857.73707305847555.838452999
1147916.48847443847555.1467102461147918.48788216847555.098041006
1147977.78691878847553.374671987 1148068.3181604847557.862793672
#Sta/Elev= 30
9849.043149.70799859.761146.00249863.053144.56819869.636141.03459882.803133.4236
9886.094132.16929889.386 132.269 9895.97133.31969899.261133.30469902.553132.7717
9912.428130.50029925.595126.8025 9935.47123.32429955.171117.30679961.734117.1368
9965.015116.51119978.139112.90449997.825109.435310001.11109.076510007.67109.6124
10014.24110.876310024.08113.884310033.93117.400910060.19128.960510086.08141.9206
10129.17 161.38710135.74164.621710145.59170.697110148.88171.412210150.97171.3211
#Mann= 3 , 0 , 0
9849.043    0.12       09849.043    0.12       010150.97    0.12       0
#XS Ineff= 2 , 0
       0                               0
Bank Sta=9849.043,10150.97
Exp/Cntr=0.3,0.1

Type RM Length L Ch R = 1 ,3010.659,49.826500,49.826500,49.826500
XS GIS Cut Line= 6
1147777.02530676847613.3819729731147873.00569868847614.707576971
1147903.71791987847610.3091812321147980.16034085847591.675773526
1148021.64206022847588.5029215461148076.07245719847588.784725657
#Sta/Elev= 30
9849.057 129.5819869.256 132.6979872.541131.61179898.814119.2976 9915.23112.6535
9918.512111.82619928.359 112.565 9954.71 112.2279964.653110.67419988.168105.9514
9994.975105.015910001.82104.635310005.24104.807210008.67105.405610015.51107.1958
10025.67110.940310039.02116.765810045.69120.259910049.03 122.44710062.27132.1588
10065.56134.127810068.85 135.56310088.59142.660810111.58153.049910127.99160.0791
10131.27161.719310137.83167.161510141.11169.457310144.39170.700110150.95172.0607
#Mann= 3 , 0 , 0
9849.057    0.12       09849.057    0.12       010150.95    0.12       0
#XS Ineff= 2 , 0
       0                               0
Bank Sta=9849.057,10150.95
Exp/Cntr=0.3,0.1

Type RM Length L Ch R = 1 ,2960.832,49.826400,49.826400,49.826400
XS GIS Cut Line= 6
1147786.88195184847650.7176728421147865.58460712847655.647882096
1147899.87147737847656.2549256121147936.49558001847652.571291176
1147991.99436013847645.7413122651148087.98648944847642.620868694
#Sta/Elev= 30
9849.042127.98069856.097126.37359865.959123.39649888.969 113.4929892.257112.1666
9895.544111.08859898.831110.79929908.693111.01839921.842110.48539948.104110.7601
9961.229108.55519971.117105.11459977.711103.05049990.90199.7760410004.1197.01406
10007.4297.2380610010.7298.7936610020.64104.059810027.25108.138310037.16114.9606
10043.77119.190910047.08120.816410050.38121.606110060.26127.532110063.54129.2921
10093.09143.096810116.07152.588110125.91157.458410145.61167.939810150.96 170.614
#Mann= 3 , 0 , 0
9849.042    0.12       09849.042    0.12       010150.96    0.12       0
#XS Ineff= 2 , 0
       0                               0
Bank Sta=9849.042,10150.96
Exp/Cntr=0.3,0.1

Type RM Length L Ch R = 1 ,2911.006,49.826500,49.826500,49.826500
XS GIS Cut Line= 6
1147788.67644907847672.3829779371147879.93450775847683.467511141
  1147963.225704847710.1938720551147993.98826277847716.890689763
1148029.90005131847719.8752801591148084.75194694847718.559472106
#Sta/Elev= 30
9849.034126.45479857.599122.92149864.189121.07719883.961112.96749887.256111.9363
9893.847111.47139920.354108.52869940.293108.33939943.671108.03289950.458106.1765
9957.244102.64979964.03198.323369983.776 93.93569991.84392.548919995.33692.27347
9998.82992.6176310002.2893.6398910005.7495.14262 10016.1101.050610019.56102.6889
 10036.6109.199610043.31110.5782 10060.1115.295510076.56122.413110093.02128.1271
10099.59130.985310122.56142.056310129.13145.388410135.69149.106810150.94 155.581
#Mann= 3 , 0 , 0
9849.034    0.12       09849.034    0.12       010150.94    0.12       0
#XS Ineff= 2 , 0
       0                               0
Bank Sta=9849.034,10150.94
Exp/Cntr=0.3,0.1

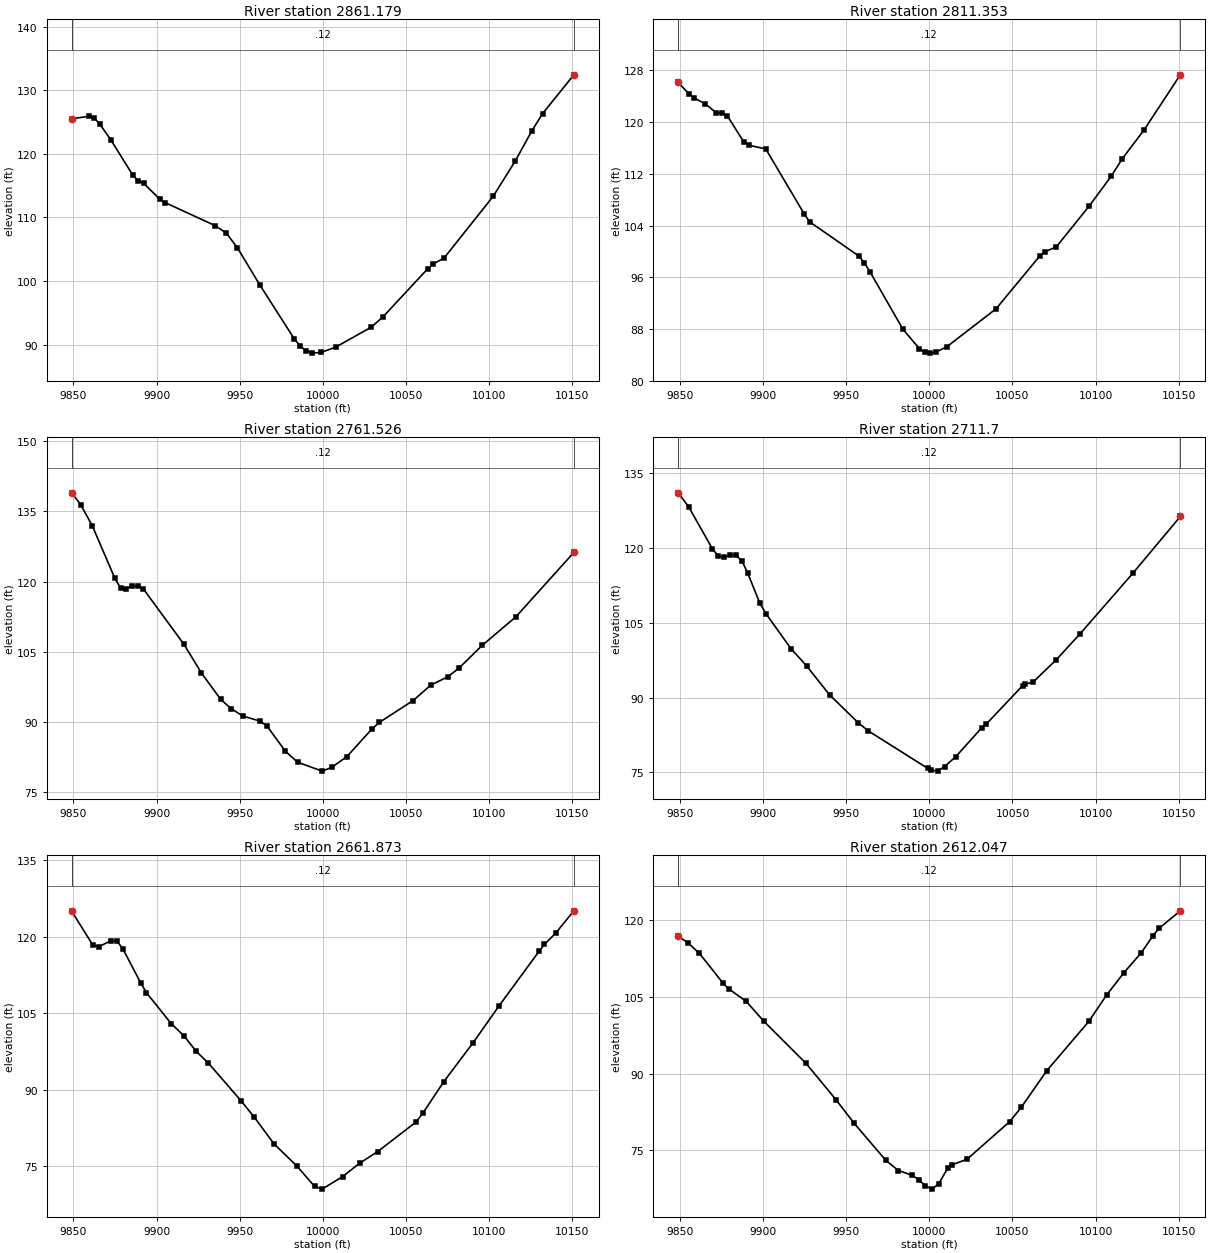
Type RM Length L Ch R = 1 ,2861.179,49.826500,49.826500,49.826500
XS GIS Cut Line= 6
1147760.68539948847714.4570633841147815.86950956847718.112524171
1147861.22233629847725.2839665131147965.07249076847760.929931203
1148001.08011136 847763.590537211148055.45046413847759.929738437
#Sta/Elev= 30
9849.058125.52559859.352125.8988 9862.64125.61739865.928124.67649872.505122.2124
9885.657116.69639888.945115.78669892.233115.38359902.097112.85779905.395112.3144
 9935.29108.71619941.933107.56029948.576105.25889962.224 99.3529 9982.9290.88515
9986.45589.77593 9989.9989.038559993.52488.68306    999988.7963510007.7189.62618
10029.0392.7482910036.06 94.361710063.04101.940410066.33102.692410072.91103.6393
10102.51113.371610115.66118.878510125.53123.5651 10132.1126.330710150.89 132.424
#Mann= 3 , 0 , 0
9849.058    0.12       09849.058    0.12       010150.89    0.12       0
#XS Ineff= 2 , 0
       0                               0
Bank Sta=9849.058,10150.89
Exp/Cntr=0.3,0.1

Type RM Length L Ch R = 1 ,2811.353,49.826400,49.826400,49.826400
XS GIS Cut Line= 5
1147751.43050536847806.120607885  1147900.578269847790.182835442
1147902.56115502847789.9217549471147989.04027011847781.714097943
1148051.59524772847773.281792785
#Sta/Elev= 30
9849.003126.13619855.443124.35679858.742123.72169865.341122.8032 9871.94121.4405
 9875.24121.36899878.539120.97599888.438 116.9269891.738116.41329901.636115.8592
9924.733105.81489928.032104.57919957.72899.264669961.02798.200779964.32796.84894
9984.12487.966539994.02284.967099997.32284.3727410000.6384.2608910003.9284.41443
10010.5185.2368510040.17 91.118910066.54 99.317310069.8399.9677110076.43100.7061
10096.24107.034810109.48111.6559 10116.1114.336710129.34118.846210150.99127.3184
#Mann= 3 , 0 , 0
9849.003    0.12       09849.003    0.12       010150.99    0.12       0
#XS Ineff= 2 , 0
       0                               0
Bank Sta=9849.003,10150.99
Exp/Cntr=0.3,0.1

Type RM Length L Ch R = 1 ,2761.526,49.826500,49.826500,49.826500
XS GIS Cut Line= 6
1147778.87940789847891.3539949221147826.15208288847877.388340141
1147861.43608626847864.1213592691147973.33386075847810.171038007
1148007.90973471847799.404028628 1148060.8529221 847786.74520054
#Sta/Elev= 30
9849.028138.98389854.451136.41829861.293131.99749874.977120.69269878.398118.6295
9881.819118.5046 9885.24 119.0389888.661119.03969892.082118.46419916.464106.6268
 9926.98100.50959938.59294.856689944.75692.899939951.97491.282749962.22290.21654
9966.40989.179239977.39283.813319984.80781.432259999.64479.5256110005.4180.34106
10014.4882.62454 10029.388.4443910034.0889.9514910054.3294.6103910064.8497.87929
10075.1599.6799610082.02  101.5710095.77106.370410116.02112.464910150.97126.2416
#Mann= 3 , 0 , 0
9849.028    0.12       09849.028    0.12       010150.97    0.12       0
#XS Ineff= 2 , 0
       0                               0
Bank Sta=9849.028,10150.97
Exp/Cntr=0.3,0.1

Type RM Length L Ch R = 1 ,  2711.7,49.826500,49.826500,49.826500
XS GIS Cut Line= 6
1147817.58150222847951.2121927251147859.90540736 847933.75968816
1147899.62479201847912.2508819351147971.94738188847856.472936534
 1148001.4322421847837.9962410211148080.24326867847807.323770726
#Sta/Elev= 30
9849.063131.09279855.412128.23679869.607119.85589873.156118.39149876.705118.1797
9880.253118.53579883.802118.56039887.351117.4324  9890.9114.92329898.159108.9125
 9901.89106.79499916.81499.826829926.21396.361979940.01490.549349957.296 84.9354
9963.06383.36456    999975.79297   1000175.4400310004.9575.2288110009.1876.15642
10015.8178.0901410031.41 83.886510034.2984.6859710056.1292.3875910057.5292.68163
 10062.393.0776410076.1597.5101110090.57102.769510122.33114.920910150.92126.3422
#Mann= 3 , 0 , 0
9849.063    0.12       09849.063    0.12       010150.92    0.12       0
#XS Ineff= 2 , 0
       0                               0
Bank Sta=9849.063,10150.92
Exp/Cntr=0.3,0.1

Type RM Length L Ch R = 1 ,2661.873,49.826400,49.826400,49.826400
XS GIS Cut Line= 6
1147847.74291504847990.7099052191147889.03150274847973.143828528
1147924.08021378847954.2177799741148037.56814146847874.045650222
 1148067.1805953847858.7954184591148108.92410745847842.352719844
#Sta/Elev= 30
9849.042124.95179861.862118.25139865.427118.03559872.558119.18559876.123119.1539
9879.689  117.649890.385110.97469893.952108.99399908.867102.91169916.324100.5907
9923.78197.531679931.23895.164549950.82387.793829958.71584.604879970.64679.34105
 9984.1975.062289995.00171.017179999.54270.4618810011.8872.9083810022.1775.55378
10033.0577.8400110056.1483.6491910060.0485.3049410072.7891.5540810090.2699.13308
10106.09106.456410130.29117.230210133.28118.468510140.33120.791910150.95125.0518
#Mann= 3 , 0 , 0
9849.042    0.12       09849.042    0.12       010150.95    0.12       0
#XS Ineff= 2 , 0
       0                               0
Bank Sta=9849.042,10150.95
Exp/Cntr=0.3,0.1

Type RM Length L Ch R = 1 ,2612.047,49.826500,49.826500,49.826500
XS GIS Cut Line= 6
1147873.86452638848020.3889290441147924.64957701848000.778802142
1147970.79290803847979.158189839 1148034.9977474847936.809726281
1148071.20873805847917.1215040241148143.98207758847888.309270856
#Sta/Elev= 30
9849.039116.81079854.785115.58259861.819113.46329875.976107.66999879.404 106.556
9889.954104.10069900.505100.23669925.77792.046619943.893 84.91949954.77880.32718
 9973.78 73.10099981.38171.091829989.44270.200039994.03569.212779997.53268.11588
10001.6167.45723 10005.668.4744510011.0871.5354810013.5772.2011910022.6473.27835
 10048.380.6217710055.3483.43756 10070.790.5989910095.91100.192910106.65105.3606
10117.12109.745310127.58113.649510134.56 116.95910138.05118.344410150.95121.7933
#Mann= 3 , 0 , 0
9849.039    0.12       09849.039    0.12       010150.95    0.12       0
#XS Ineff= 2 , 0
       0                               0
Bank Sta=9849.039,10150.95
Exp/Cntr=0.3,0.1

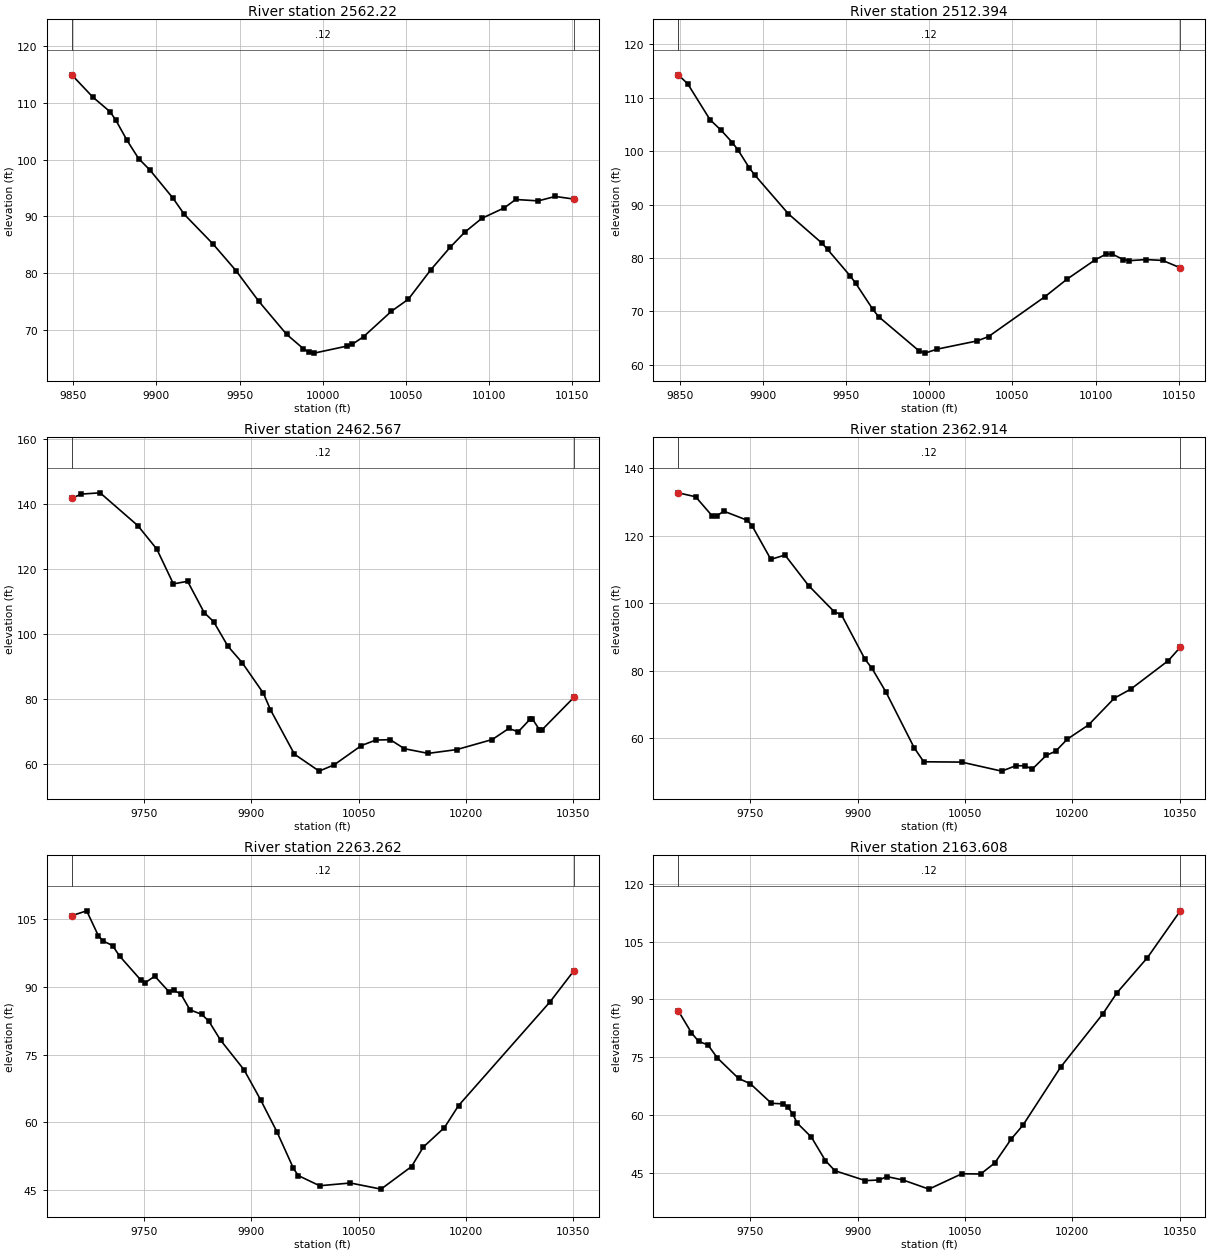
Type RM Length L Ch R = 1 , 2562.22,49.826500,49.826500,49.826500
XS GIS Cut Line= 6
 1147883.6423385848039.2037502031147987.85664517848005.744597432
1148013.65580992848000.5892977811148040.31738785847999.121078818
1148062.52868372847995.4180369461148175.50540746847965.291691965
#Sta/Elev= 30
 9849.05114.92899861.639111.02279871.977108.44769875.423106.99859882.314103.3621
9889.206100.17629896.09798.12782 9909.8893.194979916.77290.308459934.00185.09619
9947.78480.407539961.47875.012289978.20769.186249988.18766.677369991.47666.05078
9994.76665.8622510014.5267.1007510017.8467.4465610024.4968.7521710041.2773.24515
10051.4675.3708210065.0480.5914810076.6584.5450610085.4187.19159 10095.689.62074
10109.1891.4770310115.9792.9512710129.56 92.703610139.7493.4857210150.9793.02535
#Mann= 3 , 0 , 0
 9849.05    0.12       0 9849.05    0.12       010150.97    0.12       0
#XS Ineff= 2 , 0
       0                               0
Bank Sta=9849.05,10150.97
Exp/Cntr=0.3,0.1

Type RM Length L Ch R = 1 ,2512.394,49.826500,49.826500,49.826500
XS GIS Cut Line= 6
1147883.53868157848087.7492664151147983.51692921848064.762736729
1148014.45982932848055.5295555761148034.02135299848046.444148568
1148051.37795768848040.9479294881148175.00545618  848010.8079854
#Sta/Elev= 30
9849.046114.30699854.719112.63089868.185105.89459874.918103.90199881.651101.5945
9885.017100.2222 9891.7596.894969895.11695.528499915.31588.267189935.51482.77663
 9938.8881.600429952.35876.687749955.78275.266699966.05370.398539969.47769.04128
9993.87262.608949997.44962.1938110004.7662.9444410028.8864.4860710035.6465.29318
10069.4172.7283110082.9176.05822 10099.879.6733710106.5580.7713110109.9480.75389
10116.6879.7110210120.0679.5031610130.1979.7123610140.3279.5525210150.9778.17026
#Mann= 3 , 0 , 0
9849.046    0.12       09849.046    0.12       010150.97    0.12       0
#XS Ineff= 2 , 0
       0                10097.53       0
Bank Sta=9849.046,10150.97
Exp/Cntr=0.3,0.1

Type RM Length L Ch R = 1 ,2462.567,99.652900,99.652900,99.652900
XS GIS Cut Line= 6
1147705.27216814848146.2948540671147987.81313543848111.483037388
1148089.40611155848079.237236113 1148138.0348721848068.076286613
 1148269.2405859848047.8709133481148396.19017309  848034.7831259
#Sta/Elev= 30
9649.066141.67589662.317142.95889688.683143.34689741.467 133.2659767.949126.0777
9791.121115.40149810.982116.19499834.154 106.5969847.395 103.7999867.25796.29645
9887.11891.269969916.91181.863469926.84176.766659960.32763.142579994.90257.94097
10015.9659.88541 10053.965.78544 10074.167.4763710094.2467.5885110114.1664.81248
10147.3563.3909310187.1964.5475510236.8967.6383710259.9871.0328810273.1770.00998
10289.6673.8593810292.9673.9780510302.8670.6309510306.1670.5569810350.9280.55563
#Mann= 3 , 0 , 0
9649.066    0.12       09649.066    0.12       010350.92    0.12       0
#XS Ineff= 2 , 0
       0                10073.55       0
Bank Sta=9649.066,10350.92
Exp/Cntr=0.3,0.1

Type RM Length L Ch R = 1 ,2362.914,99.652900,99.652900,99.652900
XS GIS Cut Line= 6
1147690.87956674848193.0471730811147945.22571265 848178.79604438
1147995.96522749848180.6877109411148103.58277053848193.894381084
1148153.94055879848196.8765477021148391.29583607848189.171507821
#Sta/Elev= 30
9649.033132.64289673.351131.47649696.331125.84919702.902125.81759712.769127.2101
9745.658124.50919752.236122.89739778.547 112.9339798.281114.2283 9831.17105.2029
9867.31197.397749877.161  96.5549909.99383.412789919.843 80.70169939.54173.61326
9979.05857.103459992.25453.01115 10045.252.91559 10101.250.24347 10120.951.83912
10134.0351.8305510143.8750.8158710163.5654.9043610176.6856.1366310193.0959.72541
10222.6563.9211810258.77 71.850410281.7574.5238710334.2982.9768210350.9786.93869
#Mann= 3 , 0 , 0
9649.033    0.12       09649.033    0.12       010350.97    0.12       0
#XS Ineff= 2 , 0
       0                               0
Bank Sta=9649.033,10350.97
Exp/Cntr=0.3,0.1

Type RM Length L Ch R = 1 ,2263.262,99.653000,99.653000,99.653000
XS GIS Cut Line= 6
1147687.78741714848297.1181187841147789.85160286848300.483945603
1147883.77270468848298.1456707171147988.36928379848290.872310644
1148092.18593374848276.8733770521148388.11981241 848266.12727431
#Sta/Elev= 30
9649.052105.78319669.897106.8608 9686.31101.30789692.876100.16729706.006 99.1768
9715.85496.846799745.39891.552169751.96390.95248 9765.0992.383239784.78188.95306
9791.345 89.2119 9801.1988.520799814.31884.919429830.72783.917069840.57382.43349
9857.00778.213489889.89471.629789912.91665.021849935.93757.871739959.00849.77239
9965.62248.201839995.54645.9382610038.6746.5450110081.4145.18746 10124.150.19775
10140.5354.5117110170.0858.8301810189.7963.6990110317.7986.7101910350.9893.56797
#Mann= 3 , 0 , 0
9649.052    0.12       09649.052    0.12       010350.98    0.12       0
#XS Ineff= 2 , 0
       0                               0
Bank Sta=9649.052,10350.98
Exp/Cntr=0.3,0.1

Type RM Length L Ch R = 1 ,2163.608,99.652900,99.652900,99.652900
XS GIS Cut Line= 6
1147713.16415031  848382.24912951147790.29117336848389.049782335
1147876.66358592848390.2670701011147967.18830015848386.556201278
1148190.56821495848371.010277098 1148414.0990624848367.150339277
#Sta/Elev= 30
9649.05187.067919667.54581.330379677.42679.11905  9690.678.179499703.77474.79486
 9733.3969.463419749.79668.101059779.32763.005739795.73262.851639802.29562.01667
9808.85760.326039815.42157.854459835.123 54.22319854.82448.095229867.95945.48988
9910.66542.901899930.42243.06506  9940.343.961529963.34943.062459999.54640.68823
10045.56 44.683910071.8644.6180710091.5847.4883510114.5953.7180710131.02 57.3202
10183.5372.3707810242.62  86.246 10262.391.7126410304.95100.863410350.98113.0461
#Mann= 3 , 0 , 0
9649.051    0.12       09649.051    0.12       010350.98    0.12       0
#XS Ineff= 2 , 0
       0                               0
Bank Sta=9649.051,10350.98
Exp/Cntr=0.3,0.1

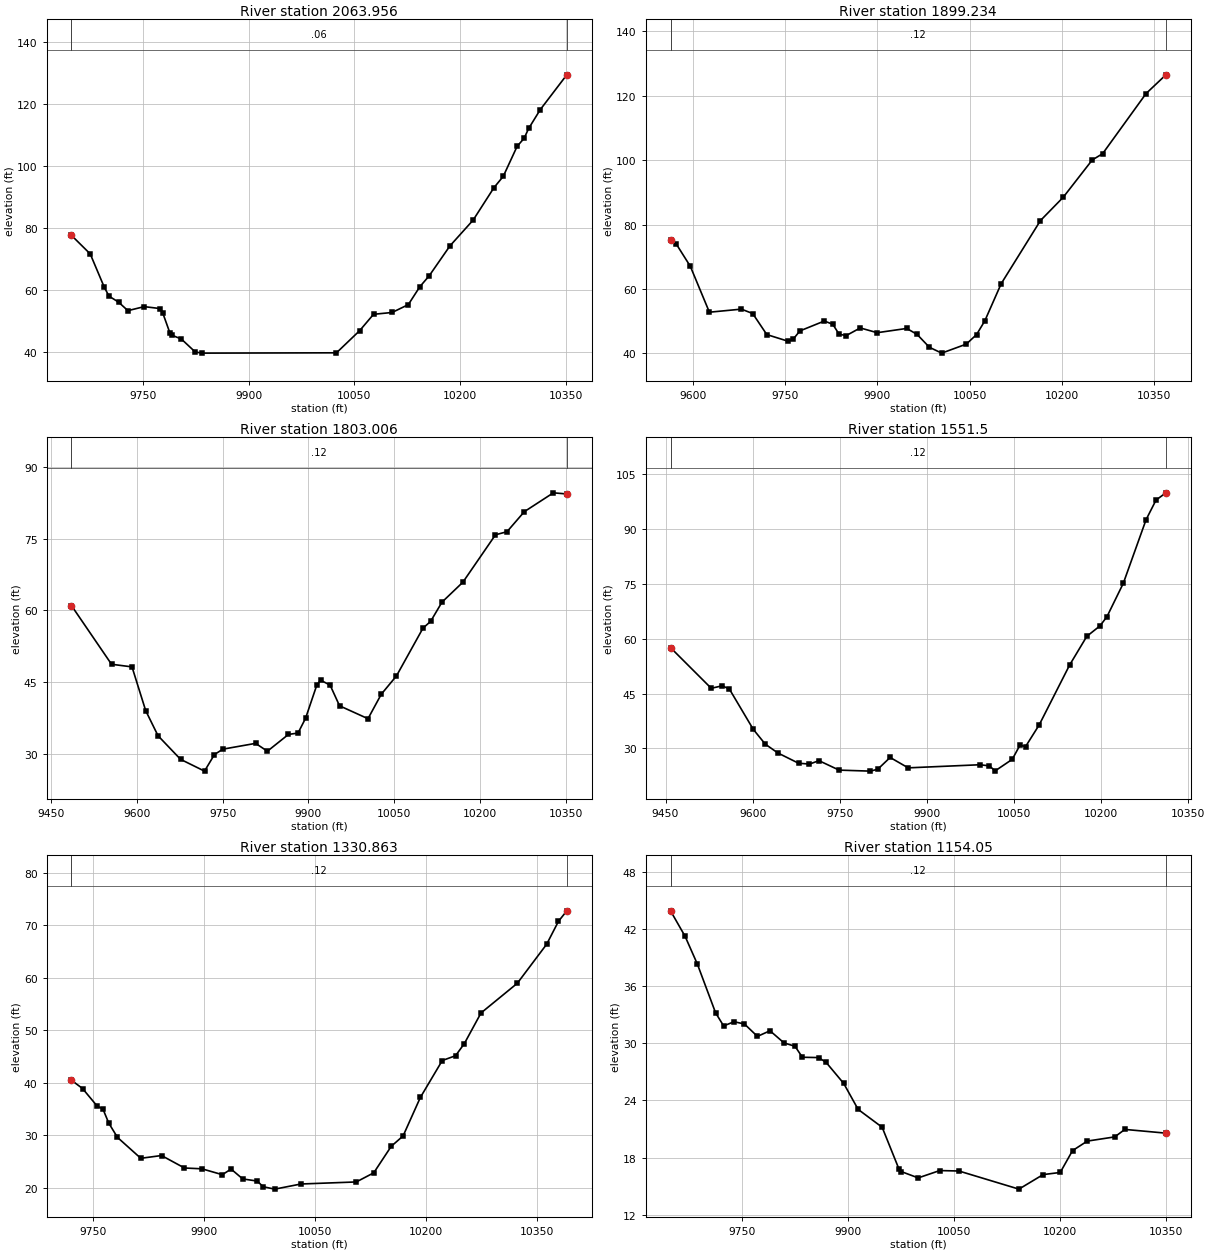
Type RM Length L Ch R = 1 ,2063.956,164.721400,164.721400,164.721400
XS GIS Cut Line= 6
1147702.12897954848454.409776401 1147778.1249354848468.680286189
1147864.24004703848475.5389554751148117.39184018848478.509078151
1148288.56024091848474.1541239921148402.33891323848475.456520383
#Sta/Elev= 30
9649.04977.746379675.684  71.7659695.71360.961749702.38958.138959715.74256.24451
9729.06253.48259 9752.1554.779249775.23254.141279778.51752.706049788.37246.42496
9791.65745.552719804.79844.342089824.49340.161039834.33639.7965910024.64 39.9001
10057.4647.0383910077.1552.31087 10103.452.8947110126.3855.4224110142.7961.20745
10155.9164.6857510185.4574.3674610218.27 82.6649 10247.893.1325410260.9396.75328
10280.62106.445510290.46 109.01310297.02112.222910313.43118.273610350.98129.4766
#Mann= 3 , 0 , 0
9649.049    0.06       09649.049    0.06       010350.98    0.06       0
#XS Ineff= 2 , 0
       09890.638                       0
Bank Sta=9649.049,10350.98
Exp/Cntr=0.3,0.1

Type RM Length L Ch R = 1 ,1899.234,96.228300,96.228300,96.228300
XS GIS Cut Line= 6
1147697.02379522848468.2317280621147805.86697015848530.211869314
1147887.49935135848598.2388536481148038.67042759848645.101887286
1148198.91176841848614.8676720411148445.31489166848672.826469284
#Sta/Elev= 30
9563.34975.13416 9572.9273.886779595.57267.025379626.59852.771359678.63353.72367
9697.04952.358139720.032 45.81959754.19843.781889762.73944.357969773.92146.96578
 9813.6850.036059827.41949.002889837.72445.915539849.30645.520969872.07247.88638
9899.551  46.4059947.63947.727219964.48645.888459984.51941.8828210004.5540.06038
10044.6242.8603510061.3145.8282810074.6650.0572210101.3761.6287710165.2781.23783
10202.3488.4782210249.53100.056610266.38102.000510337.16120.696510369.33126.4972
#Mann= 3 , 0 , 0
9563.349    0.12       09563.349    0.12       010369.33    0.12       0
#XS Ineff= 2 , 0
       0 9948.68                       0
Bank Sta=9563.349,10369.33
Exp/Cntr=0.3,0.1

Type RM Length L Ch R = 1 ,1803.006,251.506200,251.506200,251.506200
XS GIS Cut Line= 6
1147628.31399817848539.7614654881147806.20507362848656.991557091
1147892.60264072848696.4193970411147979.32127848848716.646214068
1148249.79215097848750.8807652151148440.02784833  848792.9335704
#Sta/Elev= 30
9486.119 61.00559556.10248.745879591.87648.192529615.72539.066559637.305  33.813
9676.59728.890329718.45826.422469735.78729.88322 9750.4231.008839807.65932.22133
 9828.2330.581349864.99134.089469881.68334.370949894.88937.460649914.666 44.4502
9921.25845.411099937.73944.381199954.21940.0651210003.8837.3718510027.0742.48539
10053.5646.3051710099.9356.2951610113.18 57.692910133.0661.7175510169.6265.89332
10226.4675.7868110246.5276.42468 10276.880.6152310327.5284.5514210350.9684.31327
#Mann= 3 , 0 , 0
9486.119    0.12       09486.119    0.12       010350.96    0.12       0
#XS Ineff= 2 , 0
       09921.656                       0
Bank Sta=9486.119,10350.96
Exp/Cntr=0.3,0.1

Type RM Length L Ch R = 1 ,  1551.5,220.636300,220.636300,220.636300
XS GIS Cut Line= 6
1147617.71263313848549.2244289111147662.04741061848582.583120704
1147885.57171616848750.7688845991147988.65331343848836.489370719
1147994.07866064848981.8886762711148131.88248006849176.116106808
#Sta/Elev= 30
9458.58857.589579528.72546.457559547.72247.144249560.03946.227249601.09735.22115
9621.626 31.19099643.31728.765769679.10825.947239697.88525.723289714.25526.64632
9748.90724.063749802.61623.787989815.41724.308069836.75227.528399867.80624.68377
9991.21525.5336610007.6325.2348210017.48 23.845710047.0327.0232210060.16  30.859
10070.0130.5255710093.39 36.441110145.6852.8000110175.3860.6789710197.9863.52957
10210.0566.0543510238.2175.1907310277.4492.6045910294.5397.9634710311.5299.95085
#Mann= 3 , 0 , 0
9458.588    0.12       09458.588    0.12       010311.52    0.12       0
#XS Ineff= 2 , 0
       09875.227                       0
Bank Sta=9458.588,10311.52
Exp/Cntr=0.3,0.1

Type RM Length L Ch R = 1 ,1330.863,176.813700,176.813700,176.813700
XS GIS Cut Line= 3
 1147654.4519245 848637.921662391147919.20886895849037.227217928
1148026.63074395 849194.56228739
#Sta/Elev= 30
9721.02140.508389736.05138.918829755.73435.586579763.60735.01232 9771.5532.31039
9783.28929.603869814.78125.625459842.794 26.15259873.82823.777229897.44723.62055
9925.00322.501739936.81223.575649952.558  21.693 9972.2421.286929980.11320.20785
9995.859 19.750610031.2920.7280610106.0821.11928 10129.722.8593810153.3227.91232
10169.3329.8839110192.6837.2212910222.3144.2594710240.2945.17468 10252.247.49941
10274.68  53.32310323.7158.9767510363.4466.4235110379.3370.7789610390.6372.78479
#Mann= 3 , 0 , 0
9721.021    0.12       09721.021    0.12       010390.63    0.12       0
#XS Ineff= 2 , 0
       09944.081                       0
Bank Sta=9721.021,10390.63
Exp/Cntr=0.3,0.1

Type RM Length L Ch R = 1 , 1154.05,96.213100,96.213100,96.213100
XS GIS Cut Line= 6
1147542.76421157848659.6131593761147584.89094887848724.429871377
 1147627.5470597848818.4476621611147723.96716669849157.580921161
1147749.27524935849228.3329279211147786.85812954849313.895727651
#Sta/Elev= 30
9648.241 43.89419668.93741.211999686.32438.296919712.063 33.19739723.49131.81471
9738.28532.254719753.00932.016859771.414 30.71559789.19231.307929809.07830.03038
9824.63829.679859835.094 28.5255 9858.0428.492599868.78227.98321 9893.6625.77685
9914.08123.054139948.11821.179949971.94316.792939975.34716.524689999.17715.86488
10029.7416.63595 10056.916.5885410141.9214.6865510176.1616.2111710200.45 16.4363
10217.8818.7290310238.78  19.72810277.6920.1680710292.0220.9532510350.1420.56185
#Mann= 3 , 0 , 0
9648.241    0.12       09648.241    0.12       010350.14    0.12       0
#XS Ineff= 2 , 0
       0                               0
Bank Sta=9648.241,10350.14
Exp/Cntr=0.3,0.1