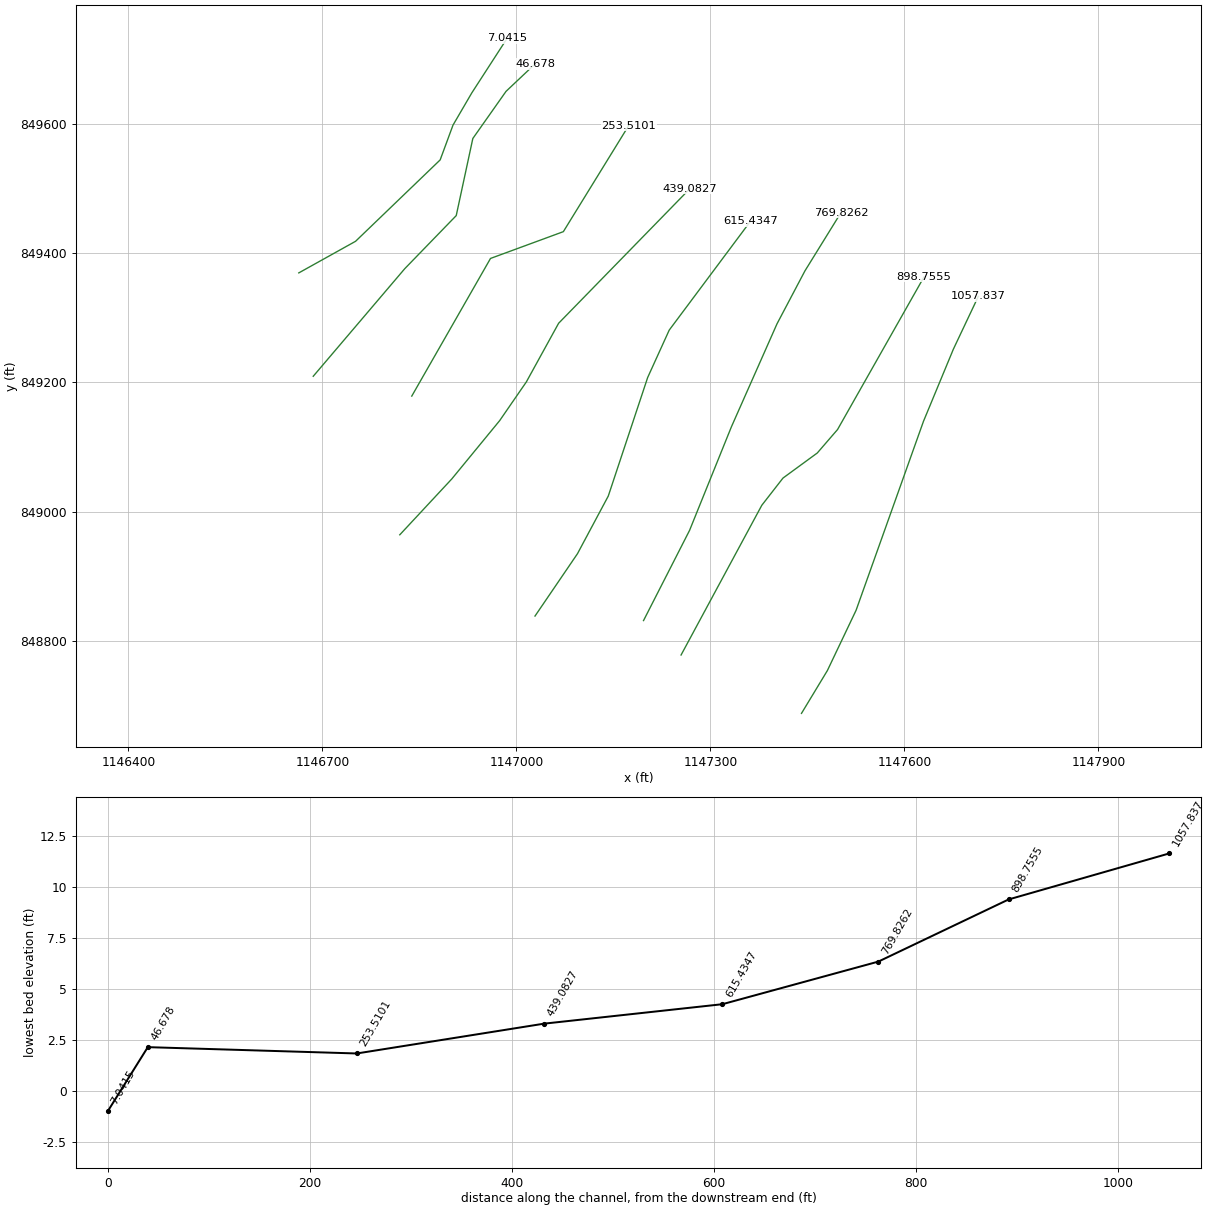
HEC-RAS study 69_ras.prj: 69

--- 69_ras.g01 (geometry) --- (continued)

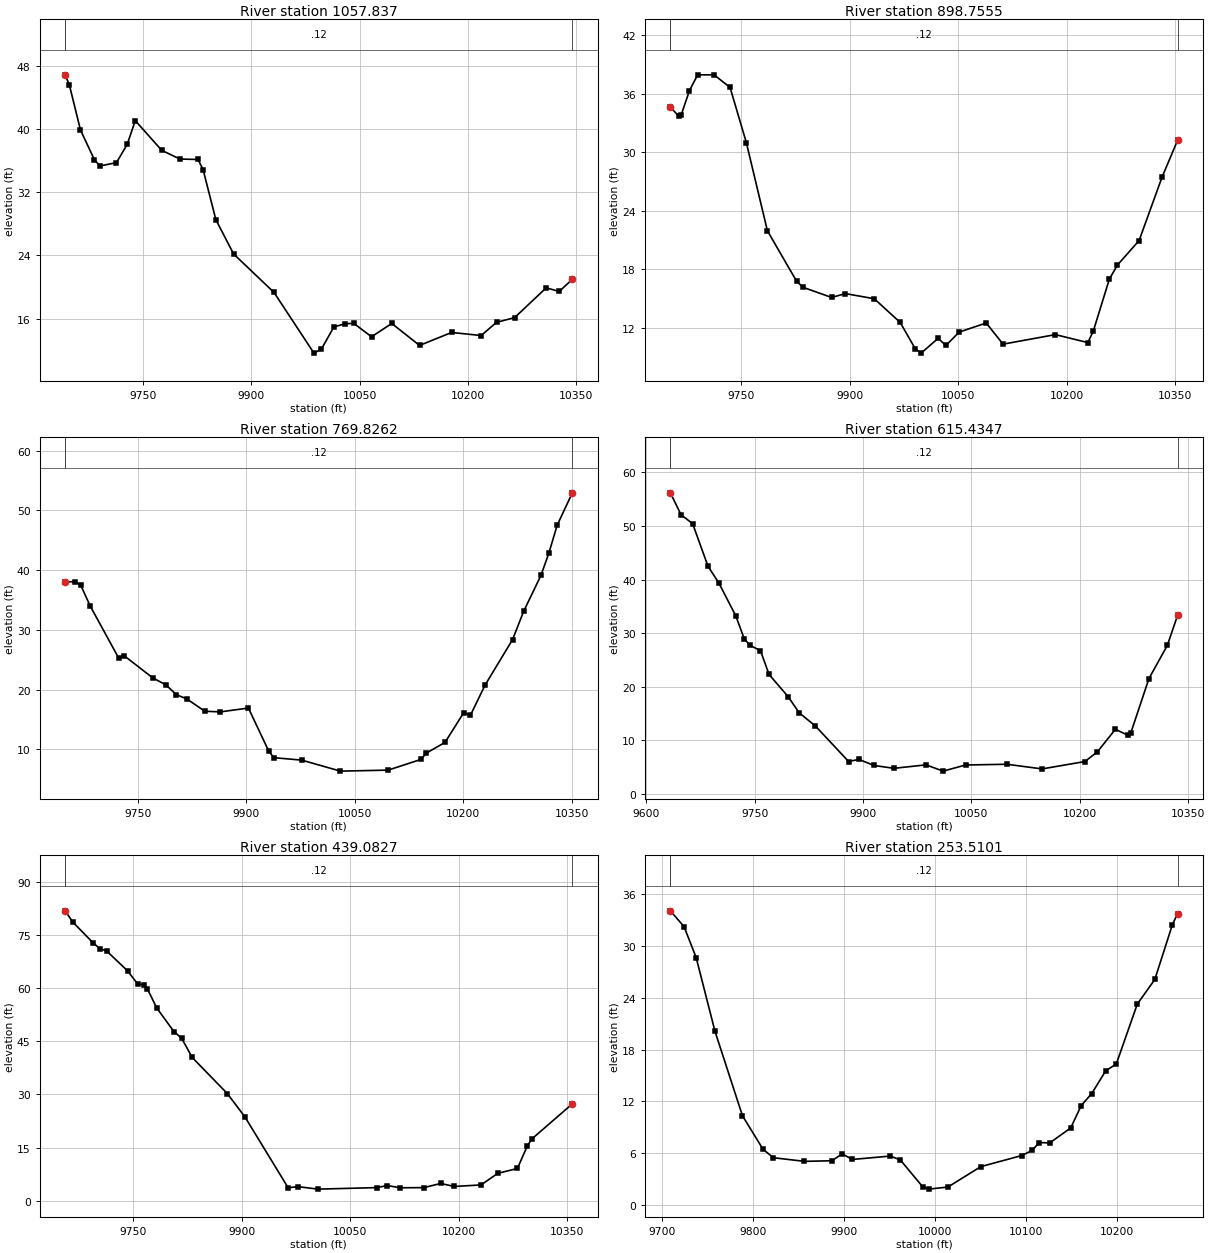
Type RM Length L Ch R = 1 ,1057.837,159.081100,159.081100,159.081100
XS GIS Cut Line= 6
1147440.84094078848688.1246462451147480.85783169848754.294669811
1147525.26921201848847.5726860681147629.47241786849139.749780041
1147675.72266995849251.3647350461147714.25558038849332.841352251
#Sta/Elev= 30
 9642.5246.828049648.334 45.5572 9663.6739.875919682.84136.123099690.50935.30868
9713.514  35.7279728.49638.062699739.54641.042589776.15837.286029801.323 36.1852
9826.41536.127249833.44634.842579851.02428.535199875.63324.186329931.56619.32351
9986.84811.652779997.17812.1731110014.3914.9517210030.0815.3803710042.0915.40532
10066.5613.7190210094.5315.4025210132.9912.62556 10177.414.2650810218.2213.87707
10239.52 15.542910264.6116.1441610308.2319.90392 10326.319.4478610344.4320.98884
#Mann= 3 , 0 , 0
 9642.52    0.12       0 9642.52    0.12       010344.43    0.12       0
#XS Ineff= 2 , 0
       0                               0
Bank Sta=9642.52,10344.43
Exp/Cntr=0.3,0.1

Type RM Length L Ch R = 1 ,898.7555,128.929300,128.929300,128.929300
XS GIS Cut Line= 6
1147254.63940707848778.3733135391147379.47928223849009.904763483
1147412.20502665849051.9450092871147465.26079717849090.746650487
1147496.58474306849127.0038925991147630.36859352849363.155712517
#Sta/Elev= 30
9651.57234.600719662.93233.723759666.70833.856959678.03636.318359689.36537.92869
9712.02237.928419734.17536.634469756.766 30.96029785.84721.940979826.44716.73824
9835.54616.130719874.72515.099789893.63715.498679933.71914.971629969.53412.54354
9990.7699.8013769998.5289.39367110022.1210.9125310032.8510.1779910051.2111.55155
10088.6612.4843810111.9110.3140610184.3511.29152 10229.210.4745110236.6811.62145
 10259.1  16.994 10270.218.4241210300.2220.9414110331.8527.4187410353.4131.21278
#Mann= 3 , 0 , 0
9651.572    0.12       09651.572    0.12       010353.41    0.12       0
#XS Ineff= 2 , 0
       0                               0
Bank Sta=9651.572,10353.41
Exp/Cntr=0.3,0.1

Type RM Length L Ch R = 1 ,769.8262,154.391500,154.391500,154.391500
XS GIS Cut Line= 6
1147196.59504707848831.6268236231147267.80454459848971.130330966
1147332.39859563849131.0451334091147402.99924384849290.491561142
1147446.18804186849372.3472244831147501.84290322849462.308543517
#Sta/Elev= 30
9649.03138.068289663.19238.028479670.617 37.45849683.75633.98184 9722.93 25.3056
9730.31525.699219770.29821.953969788.47220.783479803.01119.135459817.32518.43975
9842.283 16.36969863.67616.262299902.64616.90373 9930.789.6969599937.8138.593864
9976.498 8.1856310029.956.34409110096.046.51176210141.57 8.3122110148.729.351904
10174.7811.1578810200.51 16.114510209.9315.6948310230.1920.7513610268.1728.35624
 10283.633.1070910307.45 39.104410318.3242.7825510329.8947.4964610350.9452.93416
#Mann= 3 , 0 , 0
9649.031    0.12       09649.031    0.12       010350.94    0.12       0
#XS Ineff= 2 , 0
       0                               0
Bank Sta=9649.031,10350.94
Exp/Cntr=0.3,0.1

Type RM Length L Ch R = 1 ,615.4347,176.352000,176.352000,176.352000
XS GIS Cut Line= 6
1147028.79150044848838.6113772811147094.44602672848935.004958982
1147142.06218071849024.1048317561147203.01726508849207.516508865
1147236.33788846849280.7873817141147361.80890951849448.876832245
#Sta/Elev= 30
9633.41856.199329648.11752.117459664.23550.441149685.47542.499619700.50239.36977
9723.87633.260999735.55328.995039743.338 27.7366 9758.0826.755649769.94322.30344
9796.33518.158639811.72715.13163 9833.9912.698629880.0816.0501119894.3066.443582
9915.2395.3093589942.8684.7767159987.164 5.42389 10010.94.25318910041.955.398208
   100995.53642310147.874.66732410207.166.04579710224.457.86683410249.2812.06055
 10266.110.98615 10270.411.3003310295.7521.54172 10321.127.7022410335.3133.31966
#Mann= 3 , 0 , 0
9633.418    0.12       09633.418    0.12       010335.31    0.12       0
#XS Ineff= 2 , 0
       09938.254                       0
Bank Sta=9633.418,10335.31
Exp/Cntr=0.3,0.1

Type RM Length L Ch R = 1 ,439.0827,185.572600,185.572600,185.572600
XS GIS Cut Line= 6
1146819.72769742848964.2776755541146900.05781266849050.556120594
1146974.12302696849140.7664966731147015.40817624849200.654271163
 1147065.2844791849291.3141011311147268.19866998849499.362691454
#Sta/Elev= 30
9655.64381.791759666.15478.645499693.84972.847799703.47971.158319713.10870.45765
9741.996 64.86169755.80861.210239764.77360.878069769.25659.838319782.36454.39562
9806.09747.756199816.89545.832389831.47940.428149880.01930.256459904.41823.67021
9964.1233.7169519978.4623.98136310005.58 3.29932 10087.73.72907810101.06 4.32167
10119.623.68244410152.143.72196610175.374.90360710193.954.05232410231.124.481972
 10254.37.74671310281.529.13086410295.1215.4743910301.6217.4844110357.4927.35197
#Mann= 3 , 0 , 0
9655.643    0.12       09655.643    0.12       010357.49    0.12       0
#XS Ineff= 2 , 0
       0                               0
Bank Sta=9655.643,10357.49
Exp/Cntr=0.3,0.1

Type RM Length L Ch R = 1 ,253.5101,206.832100,206.832100,206.832100
XS GIS Cut Line= 4
1146838.25051084849178.7393103091146959.98022717849391.559290543
 1147072.6009171849432.963955954 1147173.6283007849596.926430985
#Sta/Elev= 30
9708.80834.094759723.83832.261039737.15328.683439757.85420.133869788.09110.33762
9810.7696.4448429822.1085.4772649856.1245.0553689886.3615.123051  9897.75.919293
9909.0395.2757559950.6155.6666539961.6255.2271759986.0932.1275389993.0491.835295
10014.062.079301 10050.14.43960810095.125.72649110106.696.32827710114.397.237251
10125.957.18843910149.088.92823510160.6411.52533 10172.212.9157810187.6115.56126
10199.1716.3309510222.2923.2878510241.5626.1403610260.83 32.475610266.5633.77695
#Mann= 3 , 0 , 0
9708.808    0.12       09708.808    0.12       010266.56    0.12       0
#XS Ineff= 2 , 0
       09910.777                       0
Bank Sta=9708.808,10266.56
Exp/Cntr=0.3,0.1

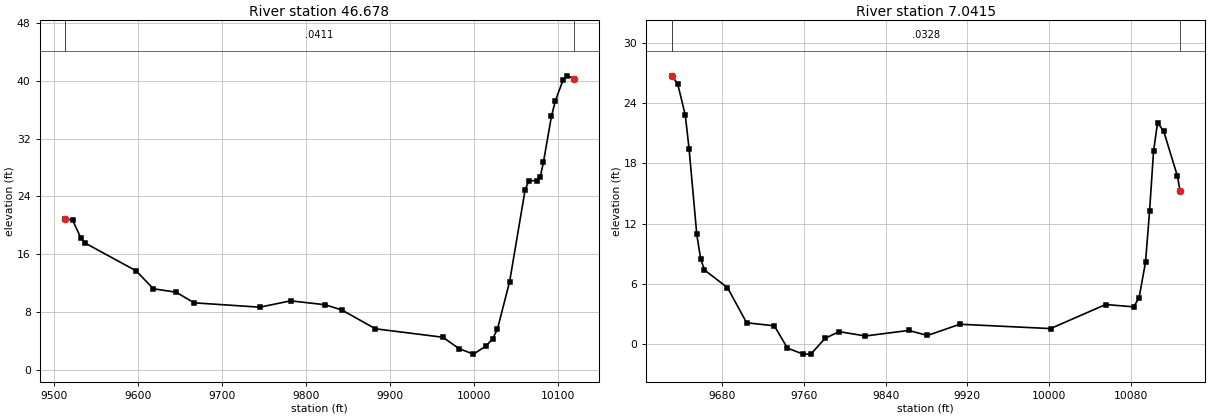
Type RM Length L Ch R = 1 ,  46.678,39.636500,39.636500,39.636500
XS GIS Cut Line= 6
1146685.88134217849209.3787627221146827.48529786849375.825517669
1146906.98225546  849457.8067552  1146932.653148 849577.05219157
1146983.99493313849649.9244026991147028.71197176849692.157161415
#Sta/Elev= 30
9513.60520.901199522.37320.720019532.49918.161949537.56217.515289598.194 13.6736
9618.57311.195269645.57610.727699667.1139.2522829745.4118.6487179781.9559.526241
9823.1018.9883529843.2228.2530699882.9695.6559629963.5134.4808119982.6392.903509
9999.7282.14595110014.753.26883710022.514.25426310028.215.56054710042.8412.18865
10061.36 24.934110065.8826.16947 10074.9  26.16810079.4126.7371610083.0628.69564
10092.62 35.066810097.3937.2642610106.4940.1060410111.73 40.693610118.9640.30491
#Mann= 3 , 0 , 0
9513.605  0.0411       09513.605  0.0411       010118.96  0.0411       0
#XS Ineff= 2 , 0
       09851.567                       0
Bank Sta=9513.605,10118.96
Exp/Cntr=0.3,0.1

Type RM Length L Ch R = 1 ,  7.0415,0.000000,0.000000,0.000000
XS GIS Cut Line= 6
1146663.52282289849369.2007712131146751.30071354  849418.0582764
1146882.13945618849543.9284592571146902.01369563849597.754524276
1146930.99696139849647.4401227831146985.65111971 849731.90564023
#Sta/Elev= 30
9630.55226.72596 9636.3625.952329643.86922.809099647.62419.416169655.13410.92338
9658.8898.5074059662.6447.3850799685.1725.6254419703.946 2.119839731.0111.824453
9743.844-0.401149759.269  -0.9999766.825  -0.9999780.6140.5705239794.4021.241184
9820.1690.8098839862.6021.3600579880.9380.8584229912.5841.97846510001.341.545326
10055.293.94233210082.653.712224   10088 4.5890410094.378.18450210098.2813.21283
10102.1919.1895110106.1222.0657410112.1621.1999910125.6316.7163110128.0915.28771
#Mann= 3 , 0 , 0
9630.552  0.0328       09630.552  0.0328       010128.09  0.0328       0
#XS Ineff= 2 , 0
       0 9896.99                       0
Bank Sta=9630.552,10128.09
Exp/Cntr=0.3,0.1